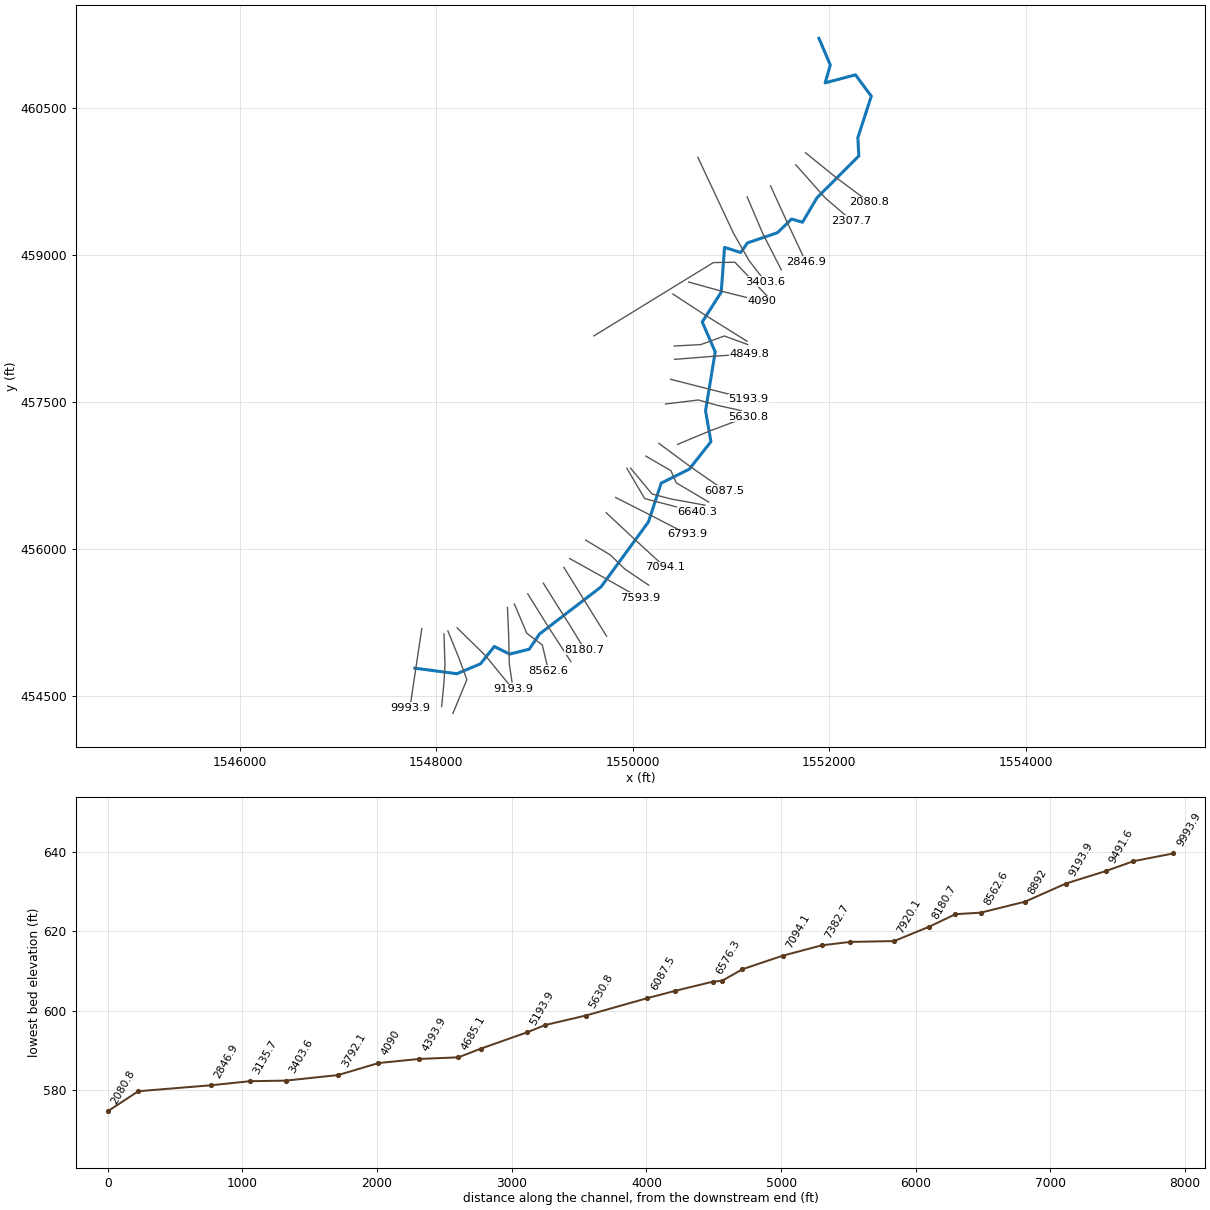
--- GARETCR.prj (project) ---

Proj Title=GARETCR
Current Plan=p01
Default Exp/Contr=0,0
English Units
Geom File=g01
Flow File=f01
Plan File=p01
BEGIN DESCRIPTION:
END DESCRIPTION:
DSS Export Rating Curves= 0
DSS Export Rating Curve Sorted= 0
DSS Export Volume Flow Curves= 0
DXF OffsetX= 0
DXF OffsetY= 0
DXF ScaleX= 0
DXF ScaleY= 0

--- GARETCR.p01 (plan) ---

Plan Title=Floodplain
Program Version=4.00
Geom File=g01
Flow File=f01
K Sum by GR=0
Std Step Tol=0.01
Critical Tol=0.01
Num of Std Step Trials=20
Max Error Tol=0.3
Flow Tol Ratio=0.001
Split Flow NTrial=30
Split Flow Tol=0.02
Split Flow Ratio=0.02
Log Output Level=0
Friction Slope Method=1
Unsteady Friction Slope Method=2
Unsteady Bridges Friction Slope Method=1
Global Log Level=0
CheckData=False
Run HTab=0
Run UNet=0
Run PostProcess=0
UNET Theta=0
UNET Theta Warmup=0
UNET ZTol=0
UNET ZSATol=0
UNET MxIter=0
UNET MaxInSteps=0
UNET DtIC=0
UNET DtMin=0
UNET MaxCRTS=0
UNET WFStab=0
UNET SFStab=0
UNET WFX=0
UNET SFX=0
UNET DSS MLevel=0
UNET DZMax Abort=0
UNET Convert EG Bridges=0
UNET Use Existing IB Tables=0
UNET Froude Limit=0
UNET Froude Power=0
Write IC File=0
Echo Input=False
Echo Output=False
Write Detailed=0

--- GARETCR.f01 (steady flow) ---

Flow Title=NFF Regression Equation
Program Version=4.00
Number of Profiles=1
Profile Names=P100yr
River Rch & RM=GARETCR,Main      ,9993.9
     355
River Rch & RM=GARETCR,Main      ,9491.6
     360
River Rch & RM=GARETCR,Main      ,9193.9
     450
River Rch & RM=GARETCR,Main      ,8892
     455
River Rch & RM=GARETCR,Main      ,7094.1
     503
River Rch & RM=GARETCR,Main      ,6793.9
     531
River Rch & RM=GARETCR,Main      ,4090
     584
River Rch & RM=GARETCR,Main      ,3792.1
     882
Boundary for River Rch & Prof#=GARETCR,Main      ,1
Up Type=0
Dn Type=3
Dn Slope=0.009534

--- GARETCR.g01 (geometry) ---

Geom Title=USGS 10m DEM
Program Version=4.00

River Reach=GARETCR         ,Main
Reach XY= 30
     1547782.499      454782.826     1548210.544      454726.244
      1548451.41      454827.574     1548591.281      455003.947
     1548747.509      454926.143     1548946.732       454976.24
     1549051.106       455130.89     1549676.683      455611.048
     1550160.778      456275.199     1550290.545      456670.797
     1550576.374      456813.139     1550796.963      457093.754
     1550742.149      457408.243     1550840.562      458009.595
     1550708.531      458315.284     1550901.639      458618.799
     1550935.626      459075.796     1551100.135      459023.702
     1551168.876      459121.346     1551475.077      459226.196
     1551617.881      459365.113     1551729.109      459332.356
     1551876.228      459580.919     1552302.675      460008.575
       1552293.1      460196.646     1552429.876      460618.764
     1552268.445      460836.378     1551959.733      460754.269
     1552012.558      460936.662     1551896.609      461208.636

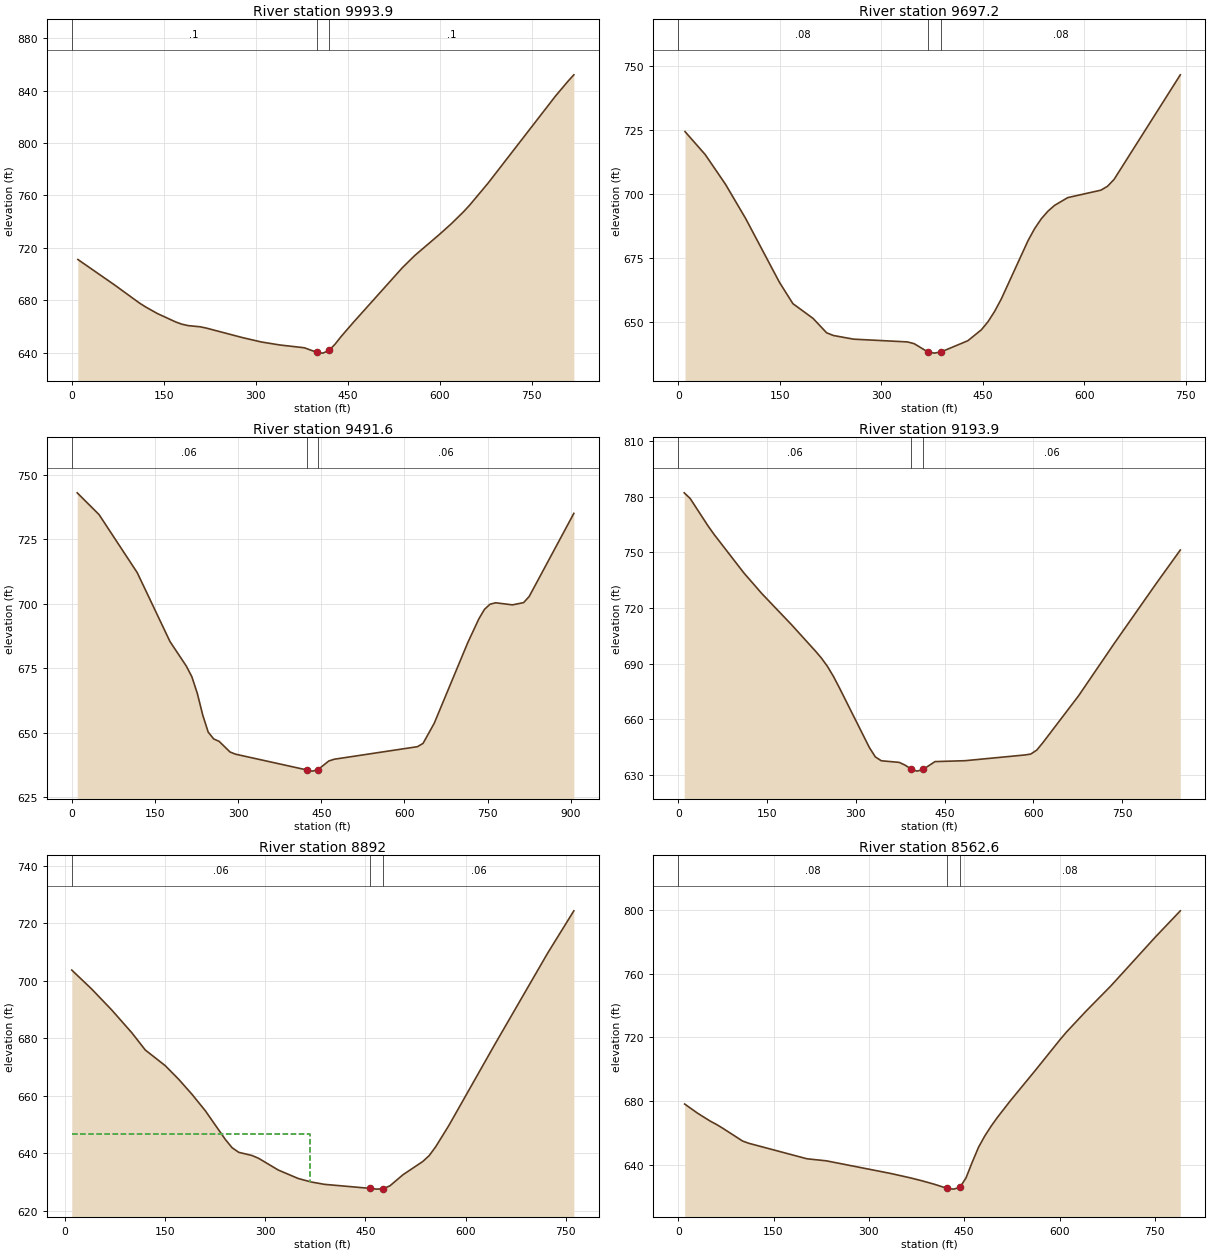
Type RM Length L Ch R = 1 ,9993.9  ,294.4,296.7,299
XS GIS Cut Line= 3
     1547852.759      455186.377      1547792.39      454781.352
     1547732.021      454376.326
#Sta/Elev= 30
      10   711.1    69.9  691.66   109.9  678.04   119.9  675.04   139.8  669.82
   169.8  663.37   179.8  661.69   189.8  660.64   209.7  659.72   219.7  658.72
   279.7  651.34   309.6  648.11   339.6  645.84   379.5  643.71   399.5  640.27
   409.5  639.63   419.5  641.64   429.5  646.48   439.5  652.37   459.4  663.14
   539.3  704.85   559.3  714.06   599.3  730.07   619.2  738.42   639.2  747.61
   649.2  752.68   679.2  769.46     789  835.83     809  846.93     819  852.08
#Mann= 3 , 0 , 0
       0      .1       0   399.5    .045       0   419.5      .1       0
Bank Sta=399.5,419.5
XS Rating Curve= 0 ,0
Exp/Cntr=0.3,0.1

Type RM Length L Ch R = 1 ,9697.2  ,196.6,205.7,216
XS GIS Cut Line= 4
     1548078.956      455132.586     1548089.241      454813.747
     1548078.956      454635.471     1548054.957      454392.057
#Sta/Elev= 30
      10  724.41    39.9   715.4    69.8  703.81    99.7  690.36   149.5  665.45
   169.5  657.04   199.4  651.25   219.3  645.64   229.3  644.58   259.2  643.14
   338.8  642.06   348.8  641.37   368.5  638.22   378.5  637.67   388.5  638.14
   428.1  642.52     448  646.78   457.9  649.96   467.8  654.05   477.7  658.95
   517.1  681.72   526.9  686.44   536.7  690.27   546.5  693.23   556.3  695.51
   575.8  698.56   624.8  701.47   634.5  702.98   644.3  705.69   742.2  746.63
#Mann= 3 , 0 , 0
       0     .08       0   368.5    .045       0   388.5     .08       0
Bank Sta=368.5,388.5
XS Rating Curve= 0 ,0
Exp/Cntr=0.3,0.1

Type RM Length L Ch R = 1 ,9491.6  ,285.3,297.7,305.1
XS GIS Cut Line= 4
     1548118.836      455162.875     1548229.804      454889.171
     1548312.085      454666.327     1548170.111      454321.738
#Sta/Elev= 30
     9.8  742.97    49.2  734.55   118.1  712.05   177.2  685.36   206.7  675.84
   216.6  671.75   226.4  665.32   236.3  656.85   246.1  650.29     256  647.65
   265.8  646.71   285.5  642.59   295.3  641.75   423.9  635.64   433.9  635.18
   443.9  635.73   463.6  639.11   473.5  639.79   623.5  644.65   633.6  645.92
   653.8  653.73   714.2  684.91   734.3  694.17   744.4  697.84   754.5  699.84
   764.6  700.38   794.8  699.58   814.9  700.44     825   702.8   905.6  735.01
#Mann= 3 , 0 , 0
       0     .06       0   423.9    .045       0   443.9     .06       0
Bank Sta=423.9,443.9
XS Rating Curve= 0 ,0
Exp/Cntr=0.3,0.1

Type RM Length L Ch R = 1 ,9193.9  ,321.4,301.9,286
XS GIS Cut Line= 3
     1548212.662      455194.296     1548500.746      454911.595
     1548781.773      454566.904
#Sta/Elev= 30
    10.1  782.12    20.2  779.06    50.5  764.21    60.5  759.73     111  738.89
   141.3  727.77   191.7  710.91   232.1  696.69   242.2  692.89   252.3  688.44
   262.4  683.04   272.4  676.93   322.9   644.8     333  639.72   343.1  637.61
   373.4  636.74   383.4  635.25   393.6  633.15   403.6  632.02   413.6   632.9
   433.9  637.16   484.5  637.64   585.6  640.73   595.7  641.23   605.8  643.35
   615.9  647.26   676.5  672.66   737.2  701.09   807.9   733.3   848.4  751.28
#Mann= 3 , 0 , 0
       0     .06       0   393.6    .045       0   413.6     .06       0
Bank Sta=393.6,413.6
XS Rating Curve= 0 ,0
Exp/Cntr=0.3,0.1

Type RM Length L Ch R = 1 ,8892    ,306.9,329.4,352
XS GIS Cut Line= 4
     1548725.402      455402.213     1548737.204      455122.301
     1548744.061       454827.46     1548771.488      454642.328
#Sta/Elev= 30
      10  703.66      40  697.03      70  689.75   100.1  681.82   120.1  675.87
   150.1   670.4   170.1  665.69   190.1  660.45   210.1  654.72   240.1  644.73
   250.1  641.89   260.1  640.27   280.2  639.15     290  638.17   319.5  634.09
     349  631.18   368.6  629.95   388.3  629.13   456.9  627.72   466.9  627.46
   476.9  627.63   486.6   628.6   506.3  632.48   535.8  637.06   545.6  639.15
   555.4  642.26   575.1  649.66     644  677.89   722.8  709.49   762.2  724.27
#Mann= 3 , 0 , 0
      10     .06       0   456.9    .045       0   476.9     .06       0
#XS Ineff= 2 , 0
          366.69  646.71
Permanent Ineff=
       F       F
Bank Sta=456.9,476.9
XS Rating Curve= 0 ,0
Exp/Cntr=0.3,0.1

Type RM Length L Ch R = 1 ,8562.6  ,196.3,187.2,178.4
XS GIS Cut Line= 4
     1548795.486      455437.711     1548922.336      455139.443
     1549080.042      455019.449     1549141.752      454758.893
#Sta/Elev= 30
    10.1  678.16    30.4  672.41    50.6  667.37    60.8   665.2    70.9  662.73
   101.3   654.9   111.4  653.45   202.6  643.75     233  642.48     334  634.56
   363.8  631.91   383.6  629.93   403.4  627.71   423.1  625.18   433.1  624.69
   443.1  625.72   452.9  631.76   462.8  641.77   472.7  651.11   482.7  658.29
   492.6  664.38   502.5  669.89   522.3  680.04     562  699.33   601.6     719
   611.5  723.62   641.3  736.33     681  752.44   750.4  782.89   790.1  799.54
#Mann= 3 , 0 , 0
       0     .08       0   423.1    .045       0   443.1     .08       0
Bank Sta=423.1,443.1
XS Rating Curve= 0 ,0
Exp/Cntr=0.3,0.1

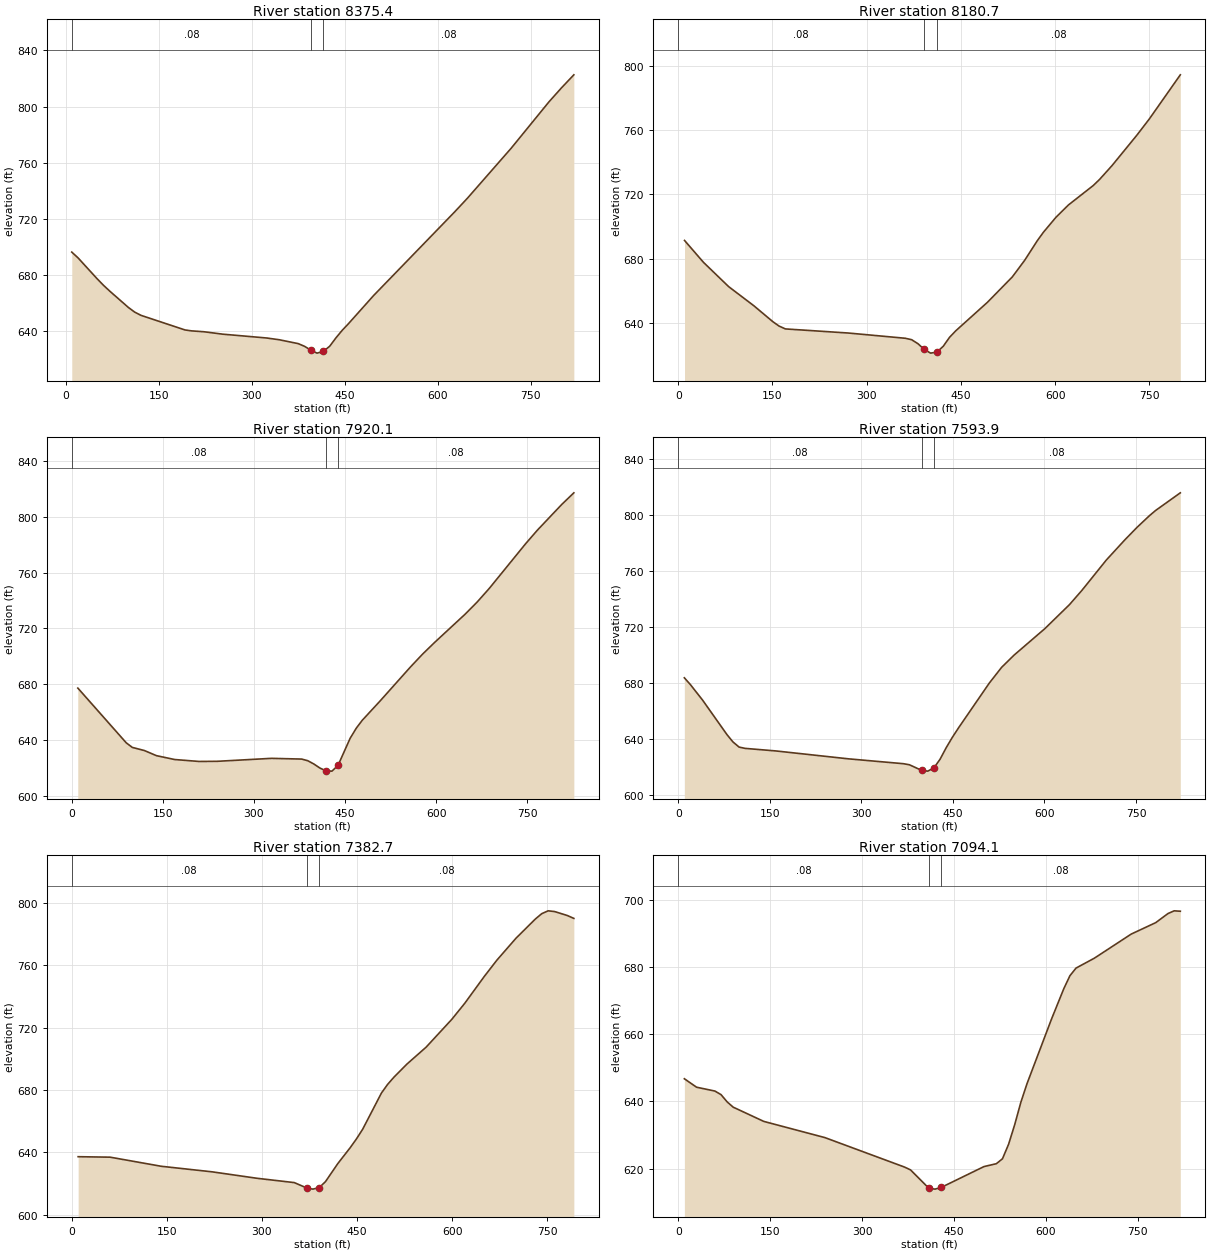
Type RM Length L Ch R = 1 ,8375.4  ,194.6,194.8,194.6
XS GIS Cut Line= 3
     1548932.203      455540.108     1549152.037       455187.44
     1549371.529      454848.829
#Sta/Elev= 30
    10.1   696.3    20.3  692.15    50.7  677.43    60.8  672.82      71  668.61
   101.4  656.83   111.5  653.54   121.6  651.24   192.6  640.82   202.7  640.19
     223  639.54   253.4  637.82   324.4  635.08   344.6  633.83     375  631.08
   385.2  629.16   395.4   626.4  405.33  624.31   415.4  625.51   425.7  629.23
   435.8   635.2   445.8  640.53   455.9  645.26   496.3  665.27   627.4  725.11
   647.6  734.68   718.2  770.35   778.7   803.2   798.9   813.2   819.1  822.62
#Mann= 3 , 0 , 0
    10.1     .08       0   395.4    .045       0   415.4     .08       0
Bank Sta=395.4,415.4
XS Rating Curve= 0 ,0
Exp/Cntr=0.3,0.1

Type RM Length L Ch R = 1 ,8180.7  ,260.9,260.6,260.4
XS GIS Cut Line= 4
     1549090.327      455650.271     1549244.604      455403.427
      1549357.74      455225.152     1549512.017      454971.452
#Sta/Elev= 30
      10  691.33    40.2  677.68    80.3  662.55   120.5  650.62   150.6  640.74
   160.6  637.98   170.6  636.23     271  633.67   361.5  630.41   371.5  629.52
   381.6  627.03   391.7  623.44   401.7  621.16   411.7  621.77   421.8  625.41
   431.9  631.02   441.9   635.1   492.2  652.81   531.9  668.66   551.7  679.09
   571.5  691.13   581.4  696.47   601.2  705.71     621  713.37   660.6  725.51
   670.5  729.23   690.3  737.83   729.9  756.78   749.7  766.86   799.2  794.44
#Mann= 3 , 0 , 0
       0     .08       0   391.7    .045       0   411.7     .08       0
Bank Sta=391.7,411.7
XS Rating Curve= 0 ,0
Exp/Cntr=0.3,0.1

Type RM Length L Ch R = 1 ,7920.1  ,313.4,326.2,338.8
XS GIS Cut Line= 3
     1549299.457      455811.404     1549514.556      455463.982
     1549734.861      455108.587
#Sta/Elev= 30
      10  677.19    89.7  637.87    99.7  634.57   119.6  632.32   139.5  628.63
   169.4  625.87   209.3  624.49   239.2  624.57   328.9  626.71   378.7  626.19
   388.7     625   398.7  622.64   408.6  619.76   418.5  617.76   428.5  617.53
   438.5  621.68   458.4   641.1   468.4   648.3   478.3  654.02   508.2  668.15
     558  692.48   577.9  701.67   597.8   710.1   647.6  730.21   667.5  738.96
   687.4  748.72   747.1  780.75     767  790.75   806.8  809.08   826.8  817.47
#Mann= 3 , 0 , 0
       0     .08       0   418.5    .045       0   438.5     .08       0
Bank Sta=418.5,438.5
XS Rating Curve= 0 ,0
Exp/Cntr=0.3,0.1

Type RM Length L Ch R = 1 ,7593.9  ,217.9,211.2,204.7
XS GIS Cut Line= 3
     1549358.634      455901.286     1549715.767      455702.458
     1550075.905       455498.77
#Sta/Elev= 30
      10  683.91    19.9  679.06    39.9  667.99    79.8   643.4    89.7  638.12
    99.7  634.47   109.7  633.55   159.5  631.74   279.1  626.08   368.9  622.62
   378.8  621.84   398.8  617.85   408.8  617.32   418.8  619.59   428.9  625.77
     439  634.05   449.1  641.46   459.2   648.2   509.7  680.21   529.8  691.38
     550  700.03   600.5  718.95   640.9  736.11     661  746.14   701.4     768
   731.7  782.37   751.9  791.39     772  799.61   782.1  803.33   822.5   815.9
#Mann= 3 , 0 , 0
       0     .08       0   398.8    .045       0   418.8     .08       0
Bank Sta=398.8,418.8
XS Rating Curve= 0 ,0
Exp/Cntr=0.3,0.1

Type RM Length L Ch R = 1 ,7382.7  ,288,288.5,289.3
XS GIS Cut Line= 4
     1549522.302      456089.103     1549772.574      455938.254
     1549919.994      455794.262     1550163.408        455629.7
#Sta/Elev= 30
    10.1  637.24    60.5  636.94   141.1  631.11   221.7  627.53   292.2  623.41
   351.1  620.64   370.5  617.23   380.5  616.46   390.5  617.48   400.2  621.23
   419.8  632.87   439.4  643.09   449.2  648.69     459  654.88   488.5  678.01
   498.3  683.58   508.4  688.26   528.7  696.57   559.1  707.47   599.6  725.29
   619.9  735.51   650.3  752.49   670.5  763.12   700.9  777.29   731.3  789.54
   741.5  793.01   751.6  794.82   761.7  794.36     782  791.79   792.1  789.96
#Mann= 3 , 0 , 0
       0     .08       0   370.5    .045       0   390.5     .08       0
Bank Sta=370.5,390.5
XS Rating Curve= 0 ,0
Exp/Cntr=0.3,0.1

Type RM Length L Ch R = 1 ,7094.1  ,293.2,300.3,306.9
XS GIS Cut Line= 3
     1549731.006      456368.637     1550029.626      456088.949
     1550331.773      455811.188
#Sta/Elev= 30
      10  646.77    29.9  644.25    59.9   643.1    69.9  642.03    79.8  639.88
    89.8  638.29   139.7  634.05   239.5  629.22   369.2  620.45   379.2   619.6
   409.2  614.11   419.2  613.86   429.2  614.36   499.2  620.59   519.3  621.44
   529.3  622.91   539.3  627.25   549.3  633.11   559.3  639.75   569.3  645.28
   609.3  664.54   629.4  673.62   639.4  677.49   649.4  679.77   679.4  682.73
   739.5  689.91   779.5  693.32   799.5  696.03   809.6  696.84   819.6  696.72
#Mann= 3 , 0 , 0
       0     .08       0   409.2    .045       0   429.2     .08       0
Bank Sta=409.2,429.2
XS Rating Curve= 0 ,0
Exp/Cntr=0.3,0.1

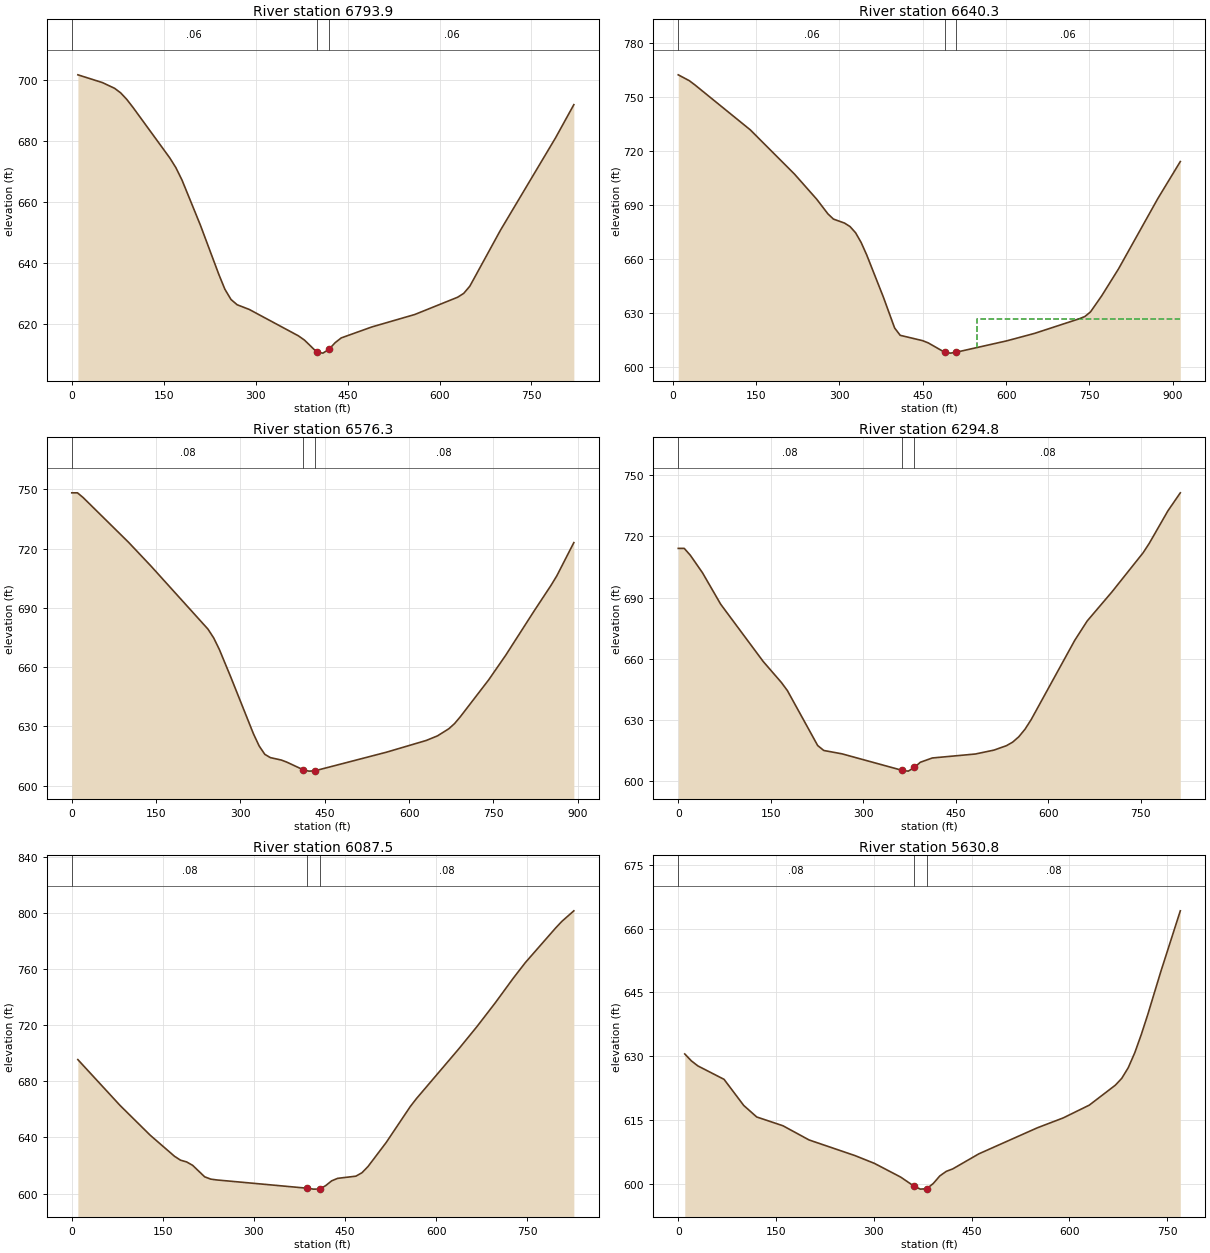
Type RM Length L Ch R = 1 ,6793.9  ,148.2,153.6,159.1
XS GIS Cut Line= 3
     1549827.306      456523.901     1550192.513      456338.273
     1550556.194      456150.159
#Sta/Elev= 30
      10  701.62      50  699.08    69.9   697.2    79.9  695.69    89.9  693.53
    99.9  690.94   159.9   674.4   169.9  671.19   179.9  667.12   209.8  652.39
   239.8  636.29   249.8  631.37   259.8  628.01   269.8  626.29   289.8  624.73
   369.7  616.11   379.7   614.7   399.7   610.8   409.7  610.44   419.7  611.69
   429.6  613.85   439.6  615.42   489.6  619.02   559.5  623.09   629.4  628.74
   639.4  630.01   649.4  632.37   699.3  650.68   789.2  680.96   819.1  691.84
#Mann= 3 , 0 , 0
       0     .06       0   399.7    .045       0   419.7     .06       0
Bank Sta=399.7,419.7
XS Rating Curve= 0 ,0
Exp/Cntr=0.3,0.1

Type RM Length L Ch R = 1 ,6640.3  ,74,64,54.7
XS GIS Cut Line= 4
     1549940.564      456822.775     1550122.672      456513.219
     1550443.965       456429.03     1550660.855      456380.745
#Sta/Elev= 30
      10  762.44    29.9  759.18    39.9  756.85   139.7  731.79   219.5  707.07
   259.4   693.1   279.3  685.04   289.3  682.12   309.3  679.89   319.2  677.94
   329.2  674.48   339.2  669.06   349.2  662.13   379.3  638.56   399.4  621.48
   409.5  617.39   449.7  614.43   459.8  613.19   490.1  607.84   500.1  607.48
   510.1  607.98   600.7  614.28     651  618.45   731.7  626.61   741.8  627.87
   751.9  630.44   772.1  639.42   802.4  654.44   873.1  693.58   913.5  714.16
#Mann= 3 , 0 , 0
      10     .06       0   490.1    .045       0   510.1     .06       0
#XS Ineff= 2 , 0
                          547.28          626.54
Permanent Ineff=
       F       F
Bank Sta=490.1,510.1
XS Rating Curve= 0 ,0
Exp/Cntr=0.3,0.1

Type RM Length L Ch R = 1 ,6576.3  ,304.3,281.5,258.7
XS GIS Cut Line= 4
     1549978.302      456823.765     1550197.703       456559.74
     1550387.355      456509.538      1550735.05      456446.321
#Sta/Elev= 30
       0  748.26    10.1  748.26    20.2  745.87     101   723.2   141.4  711.01
   242.3  679.21   252.4  674.78   262.5  668.91   282.7  655.01   323.1  626.23
   333.2  620.09   343.3  615.83   353.1  614.17   372.7  612.93   382.5  611.87
   411.8  607.97   421.8  607.32   431.8  607.44   559.7  616.91   630.3  622.84
   650.5  625.19   670.7   628.8   680.8  631.41   690.9  634.82   741.4  653.53
   771.7  665.99   822.2   688.4   852.5  701.48   862.6  706.22   892.9  723.05
#Mann= 3 , 0 , 0
       0     .08       0   411.8    .045       0   431.8     .08       0
Bank Sta=411.8,431.8
XS Rating Curve= 0 ,0
Exp/Cntr=0.3,0.1

Type RM Length L Ch R = 1 ,6294.8  ,194.5,207.3,220.8
XS GIS Cut Line= 4
     1550134.485      456946.481     1550389.214      456797.735
     1550444.994      456673.159     1550774.095       456477.93
#Sta/Elev= 30
       0  714.06     9.8  714.06    19.7  710.66    39.3  702.14    68.8  686.74
   137.7  658.71   167.2  648.42     177  644.43   226.1  617.53     236   615.1
   265.5  613.46     363  605.38     373  604.99     383   606.8   392.5  609.33
     412  611.43   481.8  613.37     512  615.29   532.2  617.45   542.2  619.17
   552.3  621.84   562.4  625.56   572.4  630.29   642.9  669.02   663.1  678.51
   703.4  692.81   753.7  711.88   763.8  716.56     794  732.45   814.1  741.27
#Mann= 3 , 0 , 0
       0     .08       0     363    .045       0     383     .08       0
Bank Sta=363,383
XS Rating Curve= 0 ,0
Exp/Cntr=0.3,0.1

Type RM Length L Ch R = 1 ,6087.5  ,431.5,456.8,480.9
XS GIS Cut Line= 3
     1550266.597      457076.505     1550594.523      456833.784
     1550938.321      456594.724
#Sta/Elev= 30
      10  695.43    79.6  662.74   129.4  641.46   169.2  626.54   179.1  623.77
   189.1  622.53     199  620.11   218.9   611.9   228.9  610.27   238.8  609.69
     388  603.78     398  603.15     408  603.19     418  605.61   427.9  609.06
   437.9  610.83   467.8  612.38   477.8  614.81   487.7  619.21   517.7  636.36
   557.5  662.05   567.5  667.63   637.3   703.1   667.2  718.97   697.1  735.75
     727  753.44     747  764.62   796.8  789.23   806.8  793.84   826.7  801.42
#Mann= 3 , 0 , 0
       0     .08       0     388    .045       0     408     .08       0
Bank Sta=388,408
XS Rating Curve= 0 ,0
Exp/Cntr=0.3,0.1

Type RM Length L Ch R = 1 ,5630.8  ,315.9,300.4,285.1
XS GIS Cut Line= 3
     1550457.505      457066.318     1550790.932      457205.536
      1551173.68      457348.942
#Sta/Elev= 30
      10  630.54    20.1  628.92    30.1  627.73    70.3  624.57   100.4  618.44
   120.4  615.72   160.6  613.66   200.7  610.32     271  606.65   301.1   604.8
   341.3  601.58   361.3  599.49   371.3  598.76   381.3  598.86   391.2  600.09
   401.2  601.86   411.2  602.94   421.1  603.52     461  607.05   550.7  613.17
   590.6  615.51   630.5  618.51   670.4  623.19   680.3  624.81   690.3  627.32
   700.3  630.84   710.2  635.09   720.2  639.81   740.1  649.86   770.1  664.19
#Mann= 3 , 0 , 0
       0     .08       0   361.3    .045       0   381.3     .08       0
Bank Sta=361.3,381.3
XS Rating Curve= 0 ,0
Exp/Cntr=0.3,0.1

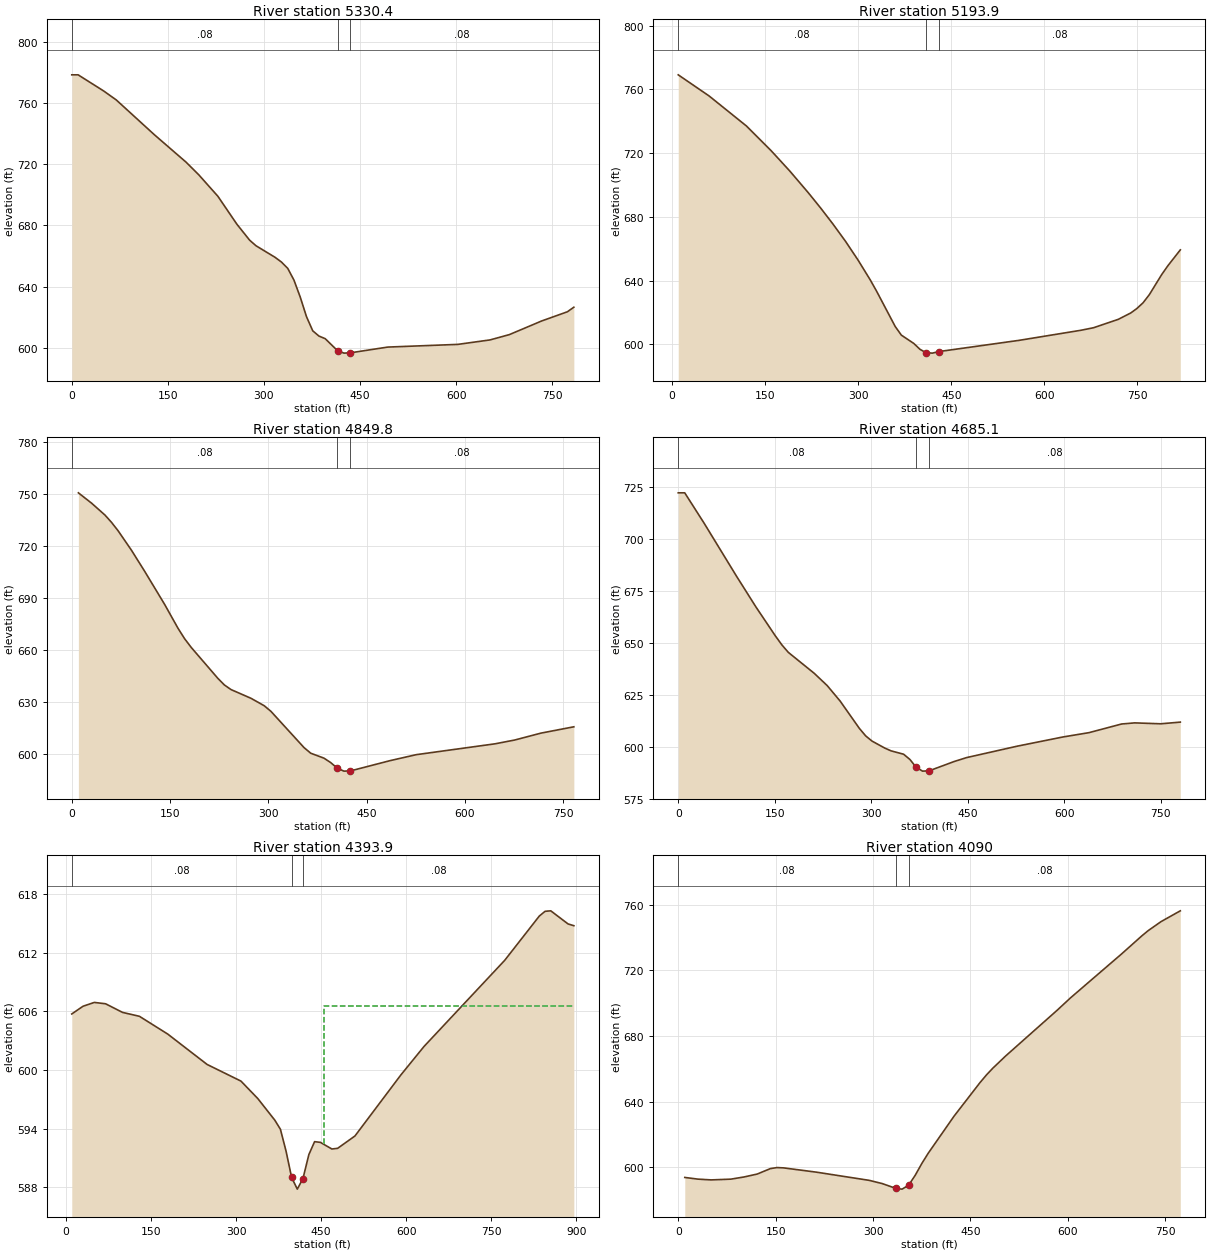
Type RM Length L Ch R = 1 ,5330.4  ,135.8,136.5,137.1
XS GIS Cut Line= 4
     1550335.293       457478.25     1550669.973      457519.155
     1550867.062      457463.375     1551103.197      457411.314
#Sta/Elev= 30
       0  778.71     9.9  778.71    49.6  768.19    69.4  762.29   128.9  739.49
   178.5  721.47   198.3   713.2   228.1  699.15   257.8  680.83   277.7  670.37
   287.6  666.73   317.3  659.17   327.3  656.06   337.2  651.88   346.9   644.2
   356.7  633.07   366.4  620.31   376.2  610.99   385.9  607.55   395.7  605.83
     415  597.94     425  596.38     435  596.58   493.2  600.34   602.5   602.1
   652.8  605.02   683.1   608.5   733.4  617.42   773.7  623.47   783.8  626.45
#Mann= 3 , 0 , 0
       0     .08       0     415    .045       0     435     .08       0
Bank Sta=415,435
XS Rating Curve= 0 ,0
Exp/Cntr=0.3,0.1

Type RM Length L Ch R = 1 ,5193.9  ,335.8,344.1,352
XS GIS Cut Line= 3
     1550386.599      457730.079     1550783.352        457628.7
     1551180.105      457527.322
#Sta/Elev= 30
      10   769.1    59.9   755.8   119.9     737   159.8  721.47   189.8  708.73
   219.7  695.08   239.7  685.43   259.7   675.3   279.7  664.58   299.6  652.98
   319.6  640.33   329.6  633.39   359.6  611.24   369.5  605.81   389.5  600.61
   399.5  596.92   409.5  594.74  419.62  594.52   429.5  595.47   559.3  602.54
   659.2  608.88   679.2  610.45   719.1  615.72   739.1   619.7   749.1  622.54
   759.1  626.14   769.1  631.21     789   643.8     799  649.35     819  659.28
#Mann= 3 , 0 , 0
      10     .08       0   409.5    .045       0   429.5     .08       0
Bank Sta=409.5,429.5
XS Rating Curve= 0 ,0
Exp/Cntr=0.3,0.1

Type RM Length L Ch R = 1 ,4849.8  ,181.3,164.7,149
XS GIS Cut Line= 3
     1550427.393      457933.569     1550851.628      457967.226
     1551191.921      457988.423
#Sta/Elev= 30
    10.1  750.79    30.4  744.78    50.7  737.97    60.8  733.72    70.9  728.84
    91.2  717.67   111.5  705.44   141.9  686.41   162.1  672.79   172.3   666.7
   182.4  661.68   222.9  643.93     233  640.05   243.2  637.39   273.6  632.38
   293.8  628.09     304  624.88   354.6  603.96   364.8  600.73     385  597.88
   395.2  595.35   405.4  592.08   415.4   590.4   425.4  590.52   485.7  596.42
   525.8  599.88   646.2  606.14   676.3  608.33   716.4  612.31   766.5  615.95
#Mann= 3 , 0 , 0
       0     .08       0   405.4    .045       0   425.4     .08       0
Bank Sta=405.4,425.4
XS Rating Curve= 0 ,0
Exp/Cntr=0.3,0.1

Type RM Length L Ch R = 1 ,4685.1  ,314.6,291.2,268.4
XS GIS Cut Line= 4
     1550422.682      458069.517     1550694.144      458084.392
     1550933.998       458171.78     1551171.992      458084.392
#Sta/Elev= 30
       0  722.41    10.1  722.41    40.3  707.74    90.6  682.23   120.8   667.4
     151  653.45   161.1  649.12   171.2  645.48   211.5  635.38   231.6  629.49
   251.7  622.03   281.7  608.82   291.5  605.21   301.3  602.72     321  599.37
   330.8  598.01   350.4  596.39   360.2  593.87   369.9  590.11   379.9  588.23
   389.9  588.35     429  592.86   448.6  594.77   527.1  600.26   598.1  604.69
   638.7  606.78   689.4  610.95   709.7  611.49   750.3  611.05   780.7  611.86
#Mann= 3 , 0 , 0
       0     .08       0   369.9    .045       0   389.9     .08       0
Bank Sta=369.9,389.9
XS Rating Curve= 0 ,0
Exp/Cntr=0.3,0.1

Type RM Length L Ch R = 1 ,4393.9  ,296.1,303.8,311.2
XS GIS Cut Line= 3
     1550409.267      458600.126     1550750.661      458376.985
     1551164.494      458118.701
#Sta/Elev= 30
     9.9  605.72    29.8  606.51    49.7   606.9    69.6  606.76    99.5  605.88
   129.3  605.48   179.1  603.67   248.7  600.56   308.4  598.86   338.2  597.07
   368.1  594.87     378  593.94     388  591.69   397.8  589.01   407.8  587.82
   417.8   588.9   428.2  591.35   438.3  592.67   448.5   592.6   468.8  591.92
     479  591.99   509.5  593.25   590.8  599.51   631.4   602.4   773.7   611.2
   834.7  615.72   844.9  616.21     855  616.26   885.5  614.92   895.7  614.74
#Mann= 3 , 0 , 0
     9.9     .08       0   397.8    .045       0   417.8     .08       0
#XS Ineff= 2 , 0
                          454.31          606.54
Permanent Ineff=
       F       F
Bank Sta=397.8,417.8
XS Rating Curve= 0 ,0
Exp/Cntr=0.3,0.1

Type RM Length L Ch R = 1 ,4090    ,290.7,297.9,305
XS GIS Cut Line= 3
      1550570.18      458722.283     1550921.921      458624.399
     1551318.057      458525.377
#Sta/Elev= 30
    10.1   593.9    30.4  592.87    50.7   592.4    81.1  592.86   101.4  594.19
   121.7  595.97     142  599.29   152.1  599.91   162.3  599.72     213  597.11
   294.1  592.13   314.4  590.14   334.8  587.29   344.8  586.78   354.8  589.12
   365.1  595.25   375.1  602.32     385   608.6   424.9  631.25   464.7  651.61
   474.7  656.32   484.6  660.47   504.5  667.96   584.2  695.95   604.1  703.26
   683.8  730.38   713.7  740.94   723.6  744.19   743.6  749.75   773.4  756.35
#Mann= 3 , 0 , 0
       0     .08       0   334.8    .045       0   354.8     .08       0
Bank Sta=334.8,354.8
XS Rating Curve= 0 ,0
Exp/Cntr=0.3,0.1

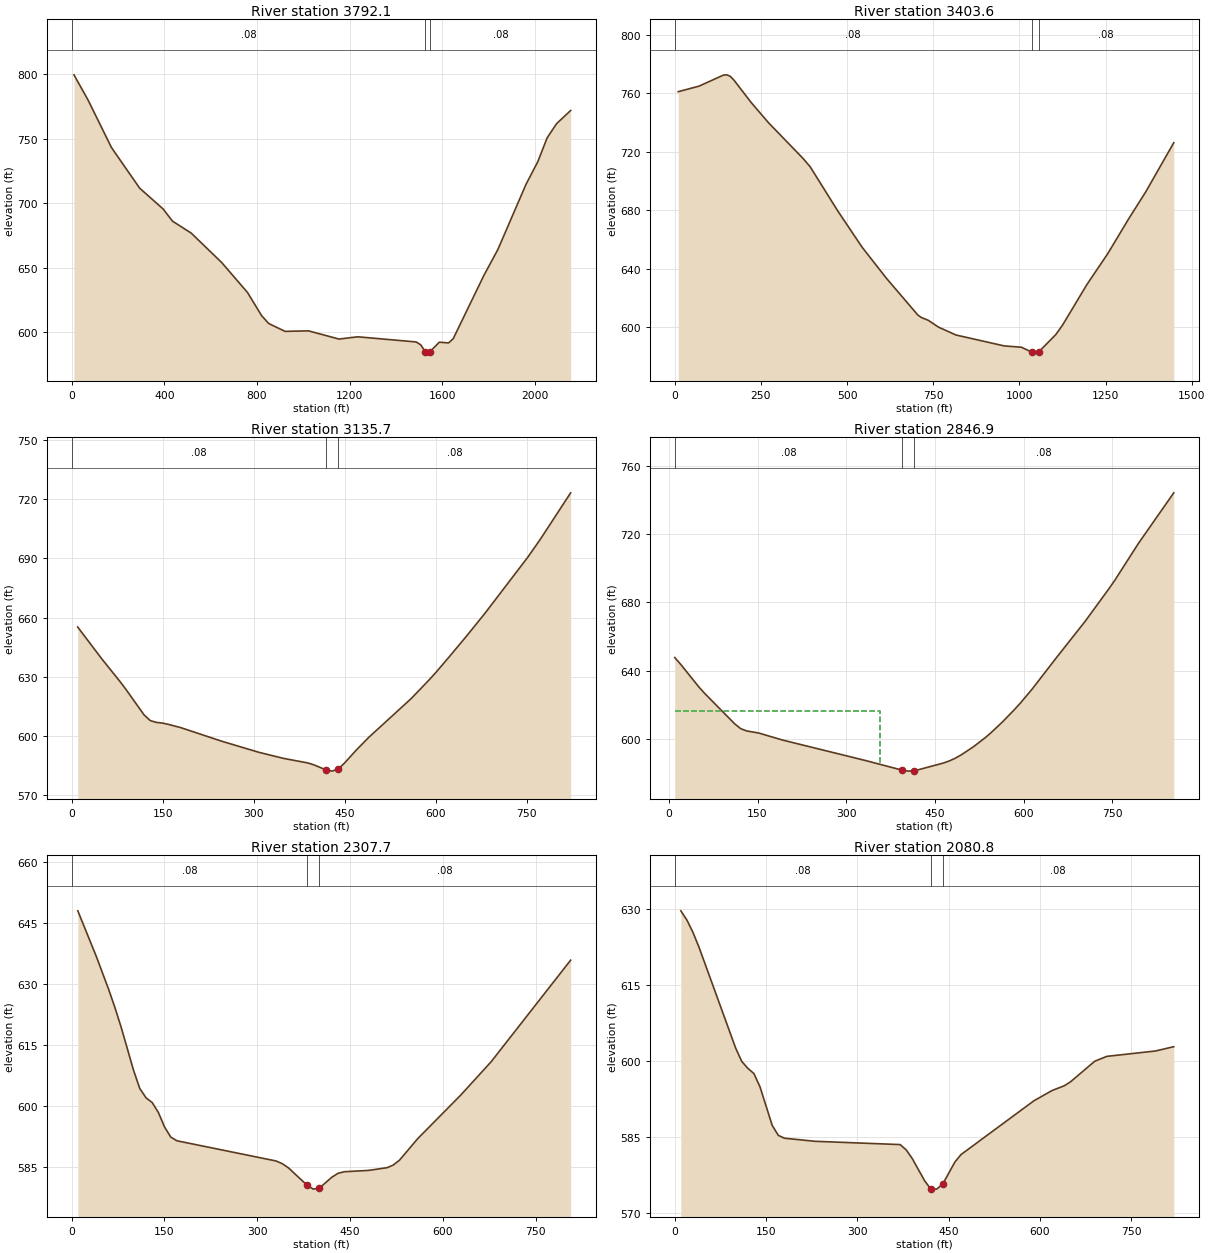
Type RM Length L Ch R = 1 ,3792.1  ,414.4,388.5,361.2
XS GIS Cut Line= 4
     1549605.949      458173.207     1550821.657      458920.941
     1551041.072      458924.369     1551390.767      458557.533
#Sta/Elev= 30
    10.1  799.52    70.9  780.01   172.1  743.11   293.5  711.68   394.8  695.54
   435.3  686.09   516.2   676.8   647.8  653.98   759.2  630.73   819.9  612.84
   850.3  606.75   921.1  600.63  1022.4  601.03  1153.9  594.66  1234.9  596.42
  1487.1  592.41  1507.1  590.11    1527  584.54    1537  583.76    1547  585.02
  1586.8  592.24  1626.7  591.68  1646.7  594.94  1778.5   643.8  1839.3  664.02
  1960.9  714.64  2011.6   732.1  2052.1  750.67  2092.7  761.63  2153.5  771.87
#Mann= 3 , 0 , 0
       0     .08       0    1527    .045       0    1547     .08       0
Bank Sta=1527,1547
XS Rating Curve= 0 ,0
Exp/Cntr=0.3,0.1

Type RM Length L Ch R = 1 ,3403.6  ,267.2,267.9,268.2
XS GIS Cut Line= 4
     1550663.924      459994.532     1551027.359       459219.21
     1551185.064      458941.511     1551351.278      458725.577
#Sta/Elev= 30
    10.1  761.15    70.5  764.95     141  772.48   151.1  772.69   161.2  771.66
   171.3  769.23   221.6  753.83     272  739.96   372.7  715.42   392.9  709.85
   473.5  679.47     544   654.7   614.5  633.49   705.2  608.49   715.2  606.75
   735.4  604.86   765.6  600.12     816  594.76   956.1   587.3    1006   586.4
  1035.9  583.07  1045.9  582.36  1055.9  583.12  1105.8  595.06  1125.7  601.64
  1195.8  629.19  1256.4  650.33  1316.9  674.08  1367.4   692.9  1448.1  726.26
#Mann= 3 , 0 , 0
       0     .08       0  1035.9    .045       0  1055.9     .08       0
Bank Sta=1035.9,1055.9
XS Rating Curve= 0 ,0
Exp/Cntr=0.3,0.1

Type RM Length L Ch R = 1 ,3135.7  ,289.6,288.9,287.8
XS GIS Cut Line= 3
      1551165.78      459590.779     1551326.044      459214.718
     1551513.918      458846.239
#Sta/Elev= 30
      10  655.25    49.9  639.05    79.8  627.61    89.7  623.55   119.6  610.64
   129.6  607.83   139.6  606.92   149.6  606.56   159.5  605.91   179.5  604.29
   249.3  597.19   309.1  591.71     349  588.68   388.8  586.39   398.8  585.44
     419  582.89     429  582.21     439   583.2   449.1  586.09   469.3  592.93
   489.5  599.27   560.1  619.13   590.4  628.87   600.5  632.29   620.6  639.53
   650.9  650.68   681.2  662.22   751.8  690.65     772  699.53   822.4  723.27
#Mann= 3 , 0 , 0
       0     .08       0     419    .045       0     439     .08       0
Bank Sta=419,439
XS Rating Curve= 0 ,0
Exp/Cntr=0.3,0.1

Type RM Length L Ch R = 1 ,2846.9  ,531.4,539.1,546.9
XS GIS Cut Line= 3
     1551403.927      459703.754     1551563.308      459353.253
     1551762.568      458929.123
#Sta/Elev= 30
    10.1  647.68    20.3  643.65    50.7  630.54    60.8  626.65   111.5  608.86
   121.6  606.04   131.7  604.71     152  603.49   192.5  599.36   334.4  587.23
     395  581.69     405  581.18     415  581.35   464.8  585.97   474.8  587.22
   484.7  588.82   494.7  590.78   514.7  595.36   534.6  600.68   544.6  603.63
   564.5  610.15   584.4  617.25   594.4  621.05   614.4  629.29   654.2  647.13
   704.1  669.02     744  687.97   753.9  692.88   793.8  714.46   853.6  744.11
#Mann= 3 , 0 , 0
    10.1     .08       0     395    .045       0     415     .08       0
#XS Ineff= 2 , 0
          356.78  616.42
Permanent Ineff=
       F       F
Bank Sta=395,415
XS Rating Curve= 0 ,0
Exp/Cntr=0.3,0.1

Type RM Length L Ch R = 1 ,2307.7  ,221.9,226.9,232.3
XS GIS Cut Line= 3
     1551661.455      459918.575     1551959.819      459580.952
     1552230.003      459349.474
#Sta/Elev= 30
      10  648.01    40.1  636.74    60.1  628.62    70.1  624.21    80.1  619.42
   100.1  608.86   110.1  604.41   120.2  602.12   130.2  600.95   140.2  598.51
   150.2  594.95   160.2  592.47   170.2  591.56   330.4   586.6   340.4  585.94
   350.4  584.91   380.5  580.65   390.5  579.69   400.5  579.96   420.5  582.61
   430.5  583.57   440.6  583.96   480.2  584.29   509.9  584.96   519.7   585.6
   529.6  586.76   559.3  592.09   628.5  602.73   677.9  610.96   806.4   635.9
#Mann= 3 , 0 , 0
       0     .08       0   380.5    .045       0   400.5     .08       0
Bank Sta=380.5,400.5
XS Rating Curve= 0 ,0
Exp/Cntr=0.3,0.1

Type RM Length L Ch R = 1 ,2080.8  ,2051.7,2080.8,2109
XS GIS Cut Line= 3
     1551760.388      460040.999     1552079.129      459782.545
     1552407.553      459538.101
#Sta/Elev= 30
      10  629.56      20  627.74      30   625.3      40  622.34   100.1  602.47
   110.1  599.84   120.1  598.48   130.1  597.44   140.1  594.82   160.1  587.23
   170.1  585.26   180.2  584.69   230.2  584.08   370.3  583.43   380.3  582.38
   390.3  580.65   410.4  576.32   420.3   574.7   430.3  574.64   440.3  575.66
   460.3     580   470.3  581.46   590.1  592.08   620.1  594.11     640  595.04
     650   595.8     690  599.88   709.9  600.84   789.8   601.9   819.8  602.75
#Mann= 3 , 0 , 0
       0     .08       0   420.3    .045       0   440.3     .08       0
Bank Sta=420.3,440.3
XS Rating Curve= 0 ,0
Exp/Cntr=0.3,0.1

Chan Stop Cuts=-1
Use User Specified Reach Order=0